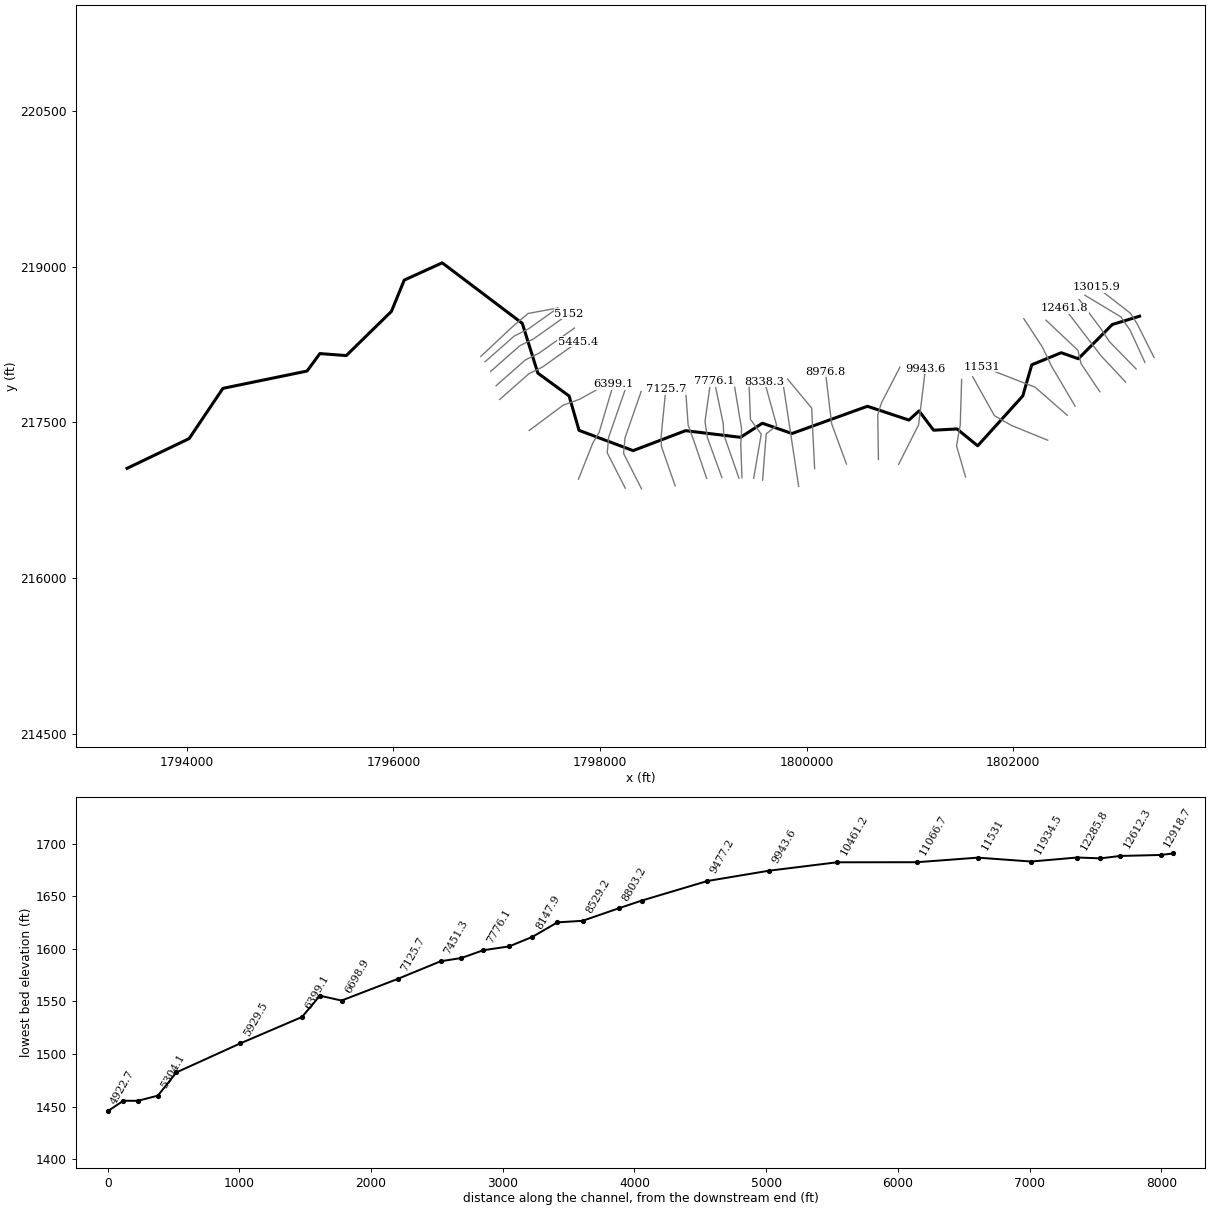
--- SkinFk.prj (project) ---

Proj Title=SkinFk
Current Plan=p01
Default Exp/Contr=0,0
English Units
Geom File=g01
Flow File=f01
Plan File=p01
BEGIN DESCRIPTION:
END DESCRIPTION:
DSS Export Rating Curves= 0
DSS Export Rating Curve Sorted= 0
DSS Export Volume Flow Curves= 0
DXF OffsetX= 0
DXF OffsetY= 0
DXF ScaleX= 0
DXF ScaleY= 0

--- SkinFk.p01 (plan) ---

Plan Title=Floodplain
Program Version=4.00
Geom File=g01
Flow File=f01
K Sum by GR=0
Std Step Tol=0.01
Critical Tol=0.01
Num of Std Step Trials=20
Max Error Tol=0.3
Flow Tol Ratio=0.001
Split Flow NTrial=30
Split Flow Tol=0.02
Split Flow Ratio=0.02
Log Output Level=0
Friction Slope Method=1
Unsteady Friction Slope Method=2
Unsteady Bridges Friction Slope Method=1
Global Log Level=0
CheckData=False
Run HTab=0
Run UNet=0
Run PostProcess=0
UNET Theta=0
UNET Theta Warmup=0
UNET ZTol=0
UNET ZSATol=0
UNET MxIter=0
UNET MaxInSteps=0
UNET DtIC=0
UNET DtMin=0
UNET MaxCRTS=0
UNET WFStab=0
UNET SFStab=0
UNET WFX=0
UNET SFX=0
UNET DSS MLevel=0
UNET DZMax Abort=0
UNET Convert EG Bridges=0
UNET Use Existing IB Tables=0
UNET Froude Limit=0
UNET Froude Power=0
Write IC File=0
Echo Input=False
Echo Output=False
Write Detailed=0

--- SkinFk.f01 (steady flow) ---

Flow Title=NFF Regression Equation
Program Version=4.00
Number of Profiles=1
Profile Names=P100yr
River Rch & RM=SkinFk,Main      ,13015.9
520.8190
River Rch & RM=SkinFk,Main      ,12918.7
757.4861
River Rch & RM=SkinFk,Main      ,11066.7
789.6308
River Rch & RM=SkinFk,Main      ,8338.3
864.1208
River Rch & RM=SkinFk,Main      ,4190.7
928.9714
River Rch & RM=SkinFk,Main      ,3903.3
1286.735
River Rch & RM=SkinFk,Main      ,149
1358.258
Boundary for River Rch & Prof#=SkinFk,Main      ,1
Up Type=0
Dn Type=3
Dn Slope=0.053745

--- SkinFk.g01 (geometry) ---

Geom Title=USGS 10m DEM
Program Version=4.00

River Reach=SkinFk          ,Main
Reach XY= 30
     1803221.835      218522.463      1802957.65      218442.407
     1802629.421      218112.577     1802463.818       218170.53
     1802178.487      218054.279     1802091.445      217753.926
     1801655.096      217273.652     1801455.355      217436.221
     1801228.519      217424.072     1801087.544      217609.826
     1800989.875      217521.764     1800587.994      217654.657
     1799857.884      217392.074     1799571.284      217491.343
     1799360.302      217355.432     1798826.998      217419.369
     1798320.811      217227.158     1797797.245      217422.495
     1797701.178      217753.926     1797398.696      217973.841
     1797248.061      218453.615     1796473.224      219036.629
     1796105.465      218870.266     1795981.576      218568.896
     1795544.471      218142.998      1795289.15      218162.327
     1795165.006      217994.094     1794350.911      217827.277
     1794024.125      217343.326     1793422.789      217056.416

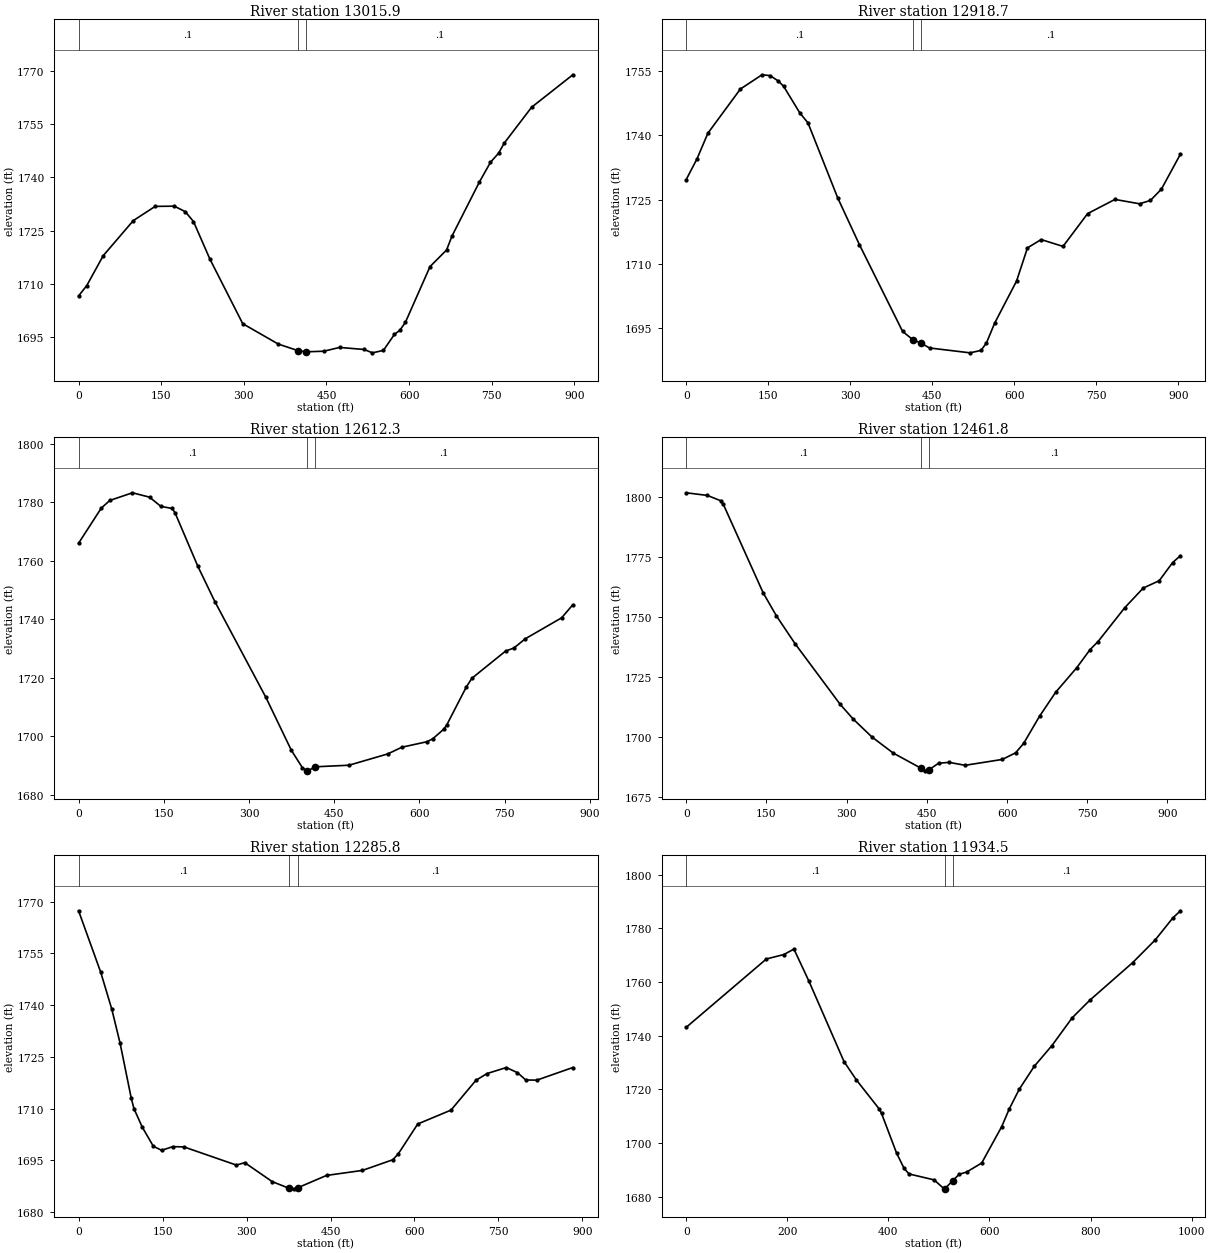
Type RM Length L Ch R = 1 ,13015.9 ,95.6,97.2,99.2
XS GIS Cut Line= 4
     1803362.016      218124.877     1803198.494      218448.513
     1803133.767      218550.714     1802806.783      218803.975
#Sta/Elev= 30
       0 1706.61    14.9 1709.53    44.7 1717.92    99.3 1727.79   139.1  1731.8
   173.8 1731.86   193.7 1730.32   208.6 1727.54   238.4 1716.98     298 1698.81
   362.6 1693.07   397.8 1691.26   412.8  1690.9   444.9 1691.06   473.9 1692.13
   518.5 1691.55   533.4 1690.61   553.3 1691.29   573.3 1695.78   583.2 1696.96
   593.2 1699.16     638 1714.87     668 1719.53   677.9 1723.47   727.7 1738.68
   747.7 1744.19   762.6 1746.79   772.6 1749.57   822.4 1759.68   897.2 1768.81
#Mann= 3 , 0 , 0
       0      .1       0   397.8    .045       0   412.8      .1       0
Bank Sta=397.8,412.8
XS Rating Curve= 0 ,0
Exp/Cntr=0.3,0.1

Type RM Length L Ch R = 1 ,12918.7 ,296.7,306.4,306.8
XS GIS Cut Line= 4
     1803273.442      218077.183     1803130.361      218387.192
     1803040.083      218516.647       1802692.6      218724.455
#Sta/Elev= 30
       0 1729.68    19.8 1734.54    39.6 1740.51      99 1750.84   138.6 1754.18
   153.4 1753.99   168.2 1752.74   178.1 1751.49   207.8 1745.25   222.7 1742.93
   277.1 1725.38   316.7 1714.46   395.7 1694.16   414.5  1692.2   429.5  1691.4
     445 1690.27   519.2 1689.13   539.2  1689.7   549.2 1691.45   564.2 1696.09
   604.2 1705.91   624.2 1713.69   649.2 1715.63   689.2 1714.03   734.2  1721.7
   784.2 1725.02   829.2    1724   849.2 1724.79   869.2 1727.43   904.1 1735.64
#Mann= 3 , 0 , 0
       0      .1       0   414.5    .045       0   429.5      .1       0
Bank Sta=414.5,429.5
XS Rating Curve= 0 ,0
Exp/Cntr=0.3,0.1

Type RM Length L Ch R = 1 ,12612.3 ,148.8,150.5,152.1
XS GIS Cut Line= 4
     1803188.274      218014.159     1802929.365      218278.178
     1802849.308      218399.116      1802636.39      218683.575
#Sta/Elev= 30
       0 1766.01      40 1778.02      55 1780.64    94.9 1783.26   124.9 1781.76
   144.9 1778.61   164.9 1777.89   169.9 1776.39   209.9 1758.16   239.9 1746.07
   329.8  1713.3   374.6 1695.22     394 1689.28   401.7 1688.23   403.6  1688.2
   416.7 1689.58   476.1 1690.12   544.4 1693.99   569.1 1696.27   613.5 1698.16
   623.4 1699.14   643.1 1702.46   648.1 1703.87   682.6 1716.87   692.5 1719.86
   751.7 1729.14   766.5  1730.2   786.2 1733.32   850.4 1740.52   870.1 1744.98
#Mann= 3 , 0 , 0
       0      .1       0   401.7    .045       0   416.7      .1       0
Bank Sta=401.7,416.7
XS Rating Curve= 0 ,0
Exp/Cntr=0.3,0.1

Type RM Length L Ch R = 1 ,12461.8 ,186.2,176,165.8
XS GIS Cut Line= 3
     1803087.121      217887.716     1802848.989      218140.719
     1802496.886      218597.672
#Sta/Elev= 30
       0 1801.65    39.7 1800.54    64.5 1798.33    69.5 1796.78   143.9 1759.99
   168.8 1750.35   203.5 1738.84   287.9 1713.58   312.7 1707.35   347.4 1699.98
   387.2 1693.29   438.1 1687.12   446.9 1685.91   453.1 1686.22   471.8 1689.07
   491.7 1689.44   521.5 1688.21   591.1 1690.66     616 1693.42   630.9  1697.3
   660.8 1708.67   690.6 1718.54   730.4 1728.87   755.2 1736.37   770.2 1739.74
   819.9 1753.77   854.7 1762.01   884.5 1765.04   909.4 1772.54   924.3 1775.51
#Mann= 3 , 0 , 0
       0      .1       0   438.1    .045       0   453.1      .1       0
Bank Sta=438.1,453.1
XS Rating Curve= 0 ,0
Exp/Cntr=0.3,0.1

Type RM Length L Ch R = 1 ,12285.8 ,345.8,351.4,356.9
XS GIS Cut Line= 4
     1802837.385      217794.427     1802655.127       218065.26
      1802626.17      218193.011      1802316.16      218484.283
#Sta/Elev= 30
       0 1767.37    39.6 1749.52    59.4  1738.8    74.2 1728.92      94 1713.09
    98.9 1709.99   113.8 1704.59   133.6 1699.05   148.4 1697.89   168.2 1698.95
     188 1698.88   281.9  1693.6   296.8 1694.31   345.8 1688.81   376.6 1686.83
   384.7 1686.71   391.6 1687.03   442.9  1690.6   506.9 1692.05   561.3 1695.15
   571.2  1696.9   605.8 1705.52   665.2 1709.55   709.7 1718.18   729.5 1720.15
   764.1  1721.9   783.9 1720.41   798.7 1718.29   818.5 1718.24   882.8  1721.9
#Mann= 3 , 0 , 0
       0      .1       0   376.6    .045       0   391.6      .1       0
Bank Sta=376.6,391.6
XS Rating Curve= 0 ,0
Exp/Cntr=0.3,0.1

Type RM Length L Ch R = 1 ,11934.5 ,336.1,403.5,424.1
XS GIS Cut Line= 4
     1802597.478      217657.102     1802372.371      218036.303
     1802282.093      218223.671     1802101.613      218498.746
#Sta/Elev= 30
       0  1743.1   158.6 1768.57   193.2 1770.22   213.1 1772.25   242.8 1760.29
   312.2 1730.33   336.9 1723.43   381.5 1712.75   386.5 1710.99   416.2 1696.23
   431.1 1690.51     441 1688.44   490.5 1686.24   510.3  1682.9   512.1 1683.02
   527.1  1685.9     540 1688.31   554.9 1689.17   584.6 1692.52   624.2 1706.06
   639.1 1712.64   658.9    1720   688.8 1728.61   723.7 1736.31   763.6 1746.62
   798.5 1753.19   883.2 1767.18   928.1 1775.69     963 1783.91     978 1786.53
#Mann= 3 , 0 , 0
       0      .1       0   512.1    .045       0   527.1      .1       0
Bank Sta=512.1,527.1
XS Rating Curve= 0 ,0
Exp/Cntr=0.3,0.1

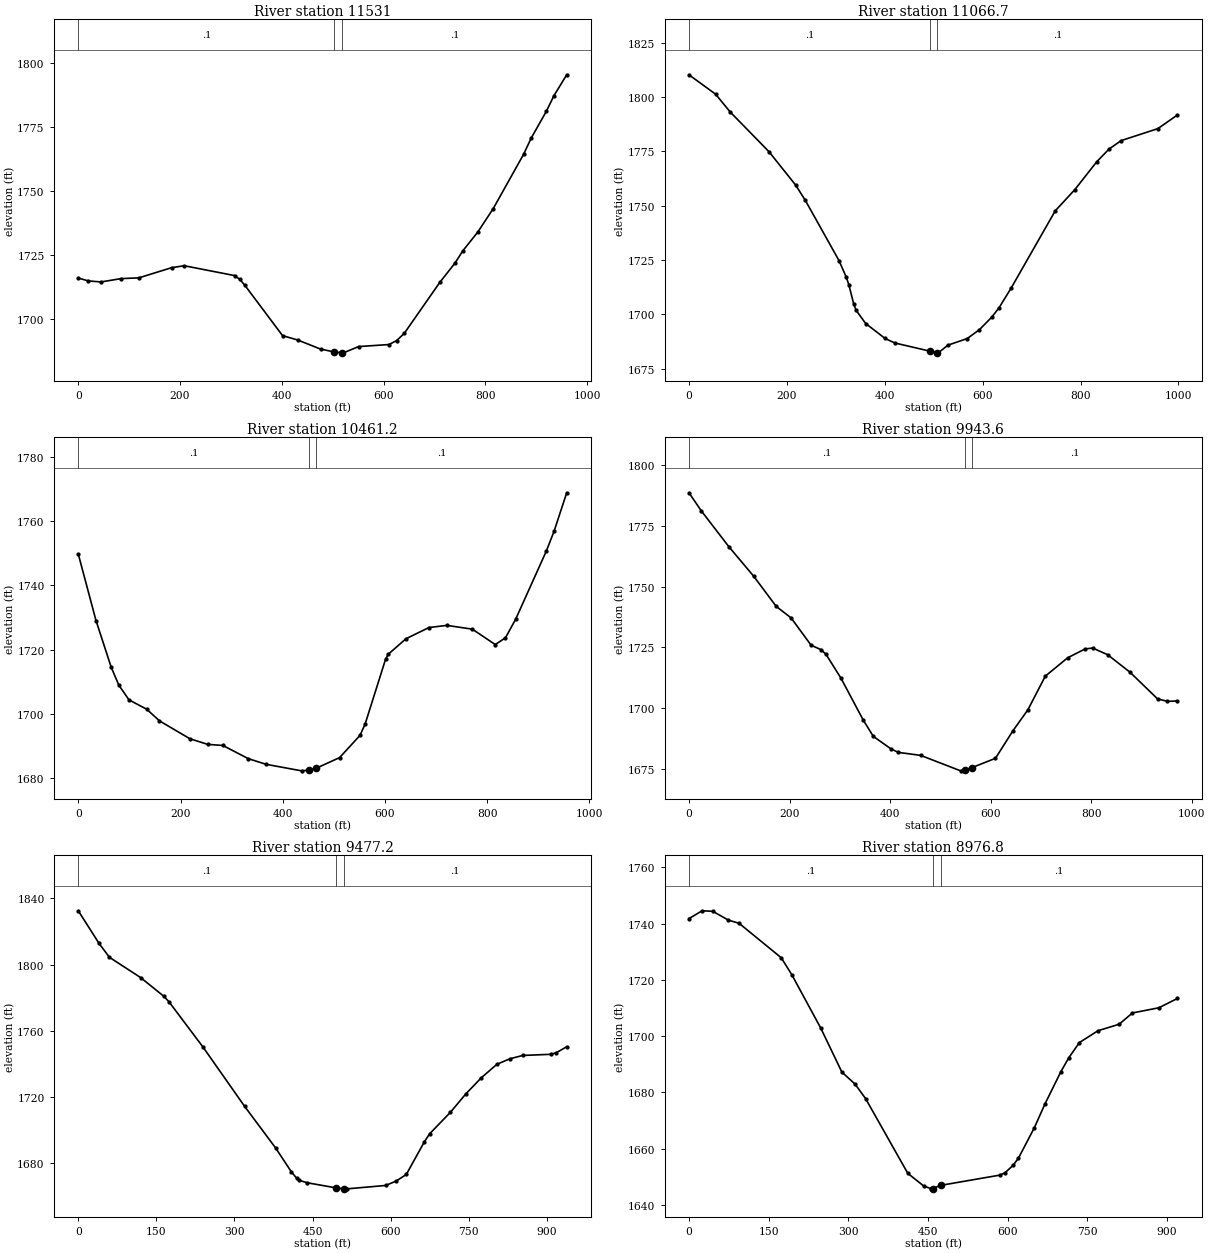
Type RM Length L Ch R = 1 ,11531   ,464.4,464.3,460.9
XS GIS Cut Line= 3
     1802520.752      217568.698     1802210.553      217838.714
     1801698.797      218036.147
#Sta/Elev= 30
       0 1715.84    19.8 1714.72    44.6 1714.32    84.2 1715.62   118.9 1715.92
   183.3 1719.89   208.1 1720.66   307.2 1716.81   317.1 1715.38     327  1713.1
   401.4 1693.32   431.2 1691.61   476.1 1688.06   503.4 1686.92   518.4 1686.62
     521 1686.59   550.9 1689.04   610.7 1689.84   625.7  1691.4   640.6 1694.22
   710.4 1714.15   740.4 1721.73   755.3  1726.4   785.2 1733.88   815.2 1742.95
     875 1764.22     890 1770.59   919.9 1781.12   934.8 1787.22   959.8 1795.35
#Mann= 3 , 0 , 0
       0      .1       0   503.4    .045       0   518.4      .1       0
Bank Sta=503.4,518.4
XS Rating Curve= 0 ,0
Exp/Cntr=0.3,0.1

Type RM Length L Ch R = 1 ,11066.7 ,638.1,605.5,574.3
XS GIS Cut Line= 4
     1802332.654      217327.455     1801979.726      217471.019
      1801817.08      217564.475     1801606.675      217938.802
#Sta/Elev= 30
       0 1810.21    54.4 1801.28    84.1 1793.12   163.3 1774.86   217.7 1759.52
   237.5 1752.51   306.8 1724.59   321.6 1716.96   326.6 1713.61   336.5 1704.82
   341.4 1701.83   361.2 1695.72   400.8 1688.84   420.5 1686.78   492.6    1683
   507.6 1682.26   509.4 1682.24   529.1 1685.77   568.6 1688.82   593.6 1692.93
   618.5 1698.64   633.5 1702.96   658.5 1712.14   748.4 1747.61   788.3 1757.33
   833.2 1770.19   858.2 1776.01   883.2 1779.93   958.1 1785.43     998 1791.71
#Mann= 3 , 0 , 0
       0      .1       0   492.6    .045       0   507.6      .1       0
Bank Sta=492.6,507.6
XS Rating Curve= 0 ,0
Exp/Cntr=0.3,0.1

Type RM Length L Ch R = 1 ,10461.2 ,518,517.5,517.6
XS GIS Cut Line= 4
      1801537.73      216973.414     1801450.334      217273.618
     1801486.225       217474.01     1801499.845      217913.193
#Sta/Elev= 30
       0 1749.78    34.7 1729.04    64.5 1714.45    79.4 1708.87    99.3 1704.29
     134 1701.38   158.8 1697.76   218.4 1692.18   253.1 1690.43   282.9 1690.08
   332.5 1685.98   367.3 1684.21   436.8 1682.17   450.8 1682.37   465.8    1683
   511.3  1686.3   551.2 1693.24   561.2 1696.77   601.1 1716.93   606.1 1718.49
   641.1 1723.37     686 1726.86     721 1727.54   770.9 1726.36   815.8 1721.56
   835.8 1723.67   855.8  1729.5   915.7 1750.72   930.7 1756.83   955.6  1768.9
#Mann= 3 , 0 , 0
       0      .1       0   450.8    .045       0   465.8      .1       0
Bank Sta=450.8,465.8
XS Rating Curve= 0 ,0
Exp/Cntr=0.3,0.1

Type RM Length L Ch R = 1 ,9943.6  ,471.4,466.4,461.1
XS GIS Cut Line= 3
     1800890.542      217096.116     1801083.393      217476.232
     1801149.737      218017.679
#Sta/Elev= 30
       0 1788.72    24.8  1781.2    79.3 1766.52   128.9  1754.3   173.5 1741.92
   203.2 1737.16   242.9 1725.92   262.7 1724.08   272.6 1722.16   302.3 1712.36
   346.9 1694.98   366.8 1688.34   401.5 1683.25   416.3 1681.76     461 1680.52
   540.3 1674.15   548.4 1674.55   563.4 1675.51   609.7 1679.31   644.4 1690.63
   674.2 1699.29   708.9 1713.17   753.5 1720.75   788.2 1724.39   803.1 1724.74
   832.9    1722   877.5 1714.76   932.1 1703.82   951.9 1702.77   971.7 1702.94
#Mann= 3 , 0 , 0
       0      .1       0   548.4    .045       0   563.4      .1       0
Bank Sta=548.4,563.4
XS Rating Curve= 0 ,0
Exp/Cntr=0.3,0.1

Type RM Length L Ch R = 1 ,9477.2  ,490.8,500.4,512.3
XS GIS Cut Line= 4
     1800694.573      217142.045      1800687.76      217571.289
      1800723.53      217687.116     1800902.382      218031.193
#Sta/Elev= 30
       0 1832.51    39.9 1812.78    59.9 1804.37   119.8 1792.12   164.7 1780.73
   174.7  1777.3   239.6 1750.12   319.5 1714.28   379.4 1688.98   409.3 1674.68
   419.3 1670.91   424.3 1669.57     439 1668.13   494.9 1664.99   509.9 1664.47
   516.6  1664.4   590.3 1666.44   610.2 1669.02   630.1 1673.07   664.9 1692.88
   674.8 1697.63   714.6 1710.58   744.4 1721.77   774.2 1731.54   804.1 1739.69
   828.9    1743   853.8 1745.05   908.5 1745.74   918.4 1746.74   938.3  1750.3
#Mann= 3 , 0 , 0
       0      .1       0   494.9    .045       0   509.9      .1       0
Bank Sta=494.9,509.9
XS Rating Curve= 0 ,0
Exp/Cntr=0.3,0.1

Type RM Length L Ch R = 1 ,8976.8  ,173.3,173.6,174
XS GIS Cut Line= 4
     1800385.136      217098.041     1800242.326      217484.418
     1800226.995      217607.059     1800181.523      217988.381
#Sta/Elev= 30
       0 1741.79    24.8 1744.56    44.7 1744.38    74.4 1741.22    94.3 1740.12
   173.7 1727.87   193.6 1721.83   248.2 1702.83   287.8 1687.24   312.7 1682.96
   332.5 1677.81   411.9 1651.26   441.6 1646.79   456.4 1645.74   458.6 1645.84
   473.6 1646.97   585.4 1650.62   595.4 1651.53   610.3 1654.12   620.3 1656.67
   650.2 1667.47   670.2 1675.93   700.1 1687.37   715.1 1692.36     735 1697.72
   769.9 1701.93   809.8 1704.23   834.8 1708.25   884.6 1710.09   919.5  1713.4
#Mann= 3 , 0 , 0
       0      .1       0   458.6    .045       0   473.6      .1       0
Bank Sta=458.6,473.6
XS Rating Curve= 0 ,0
Exp/Cntr=0.3,0.1

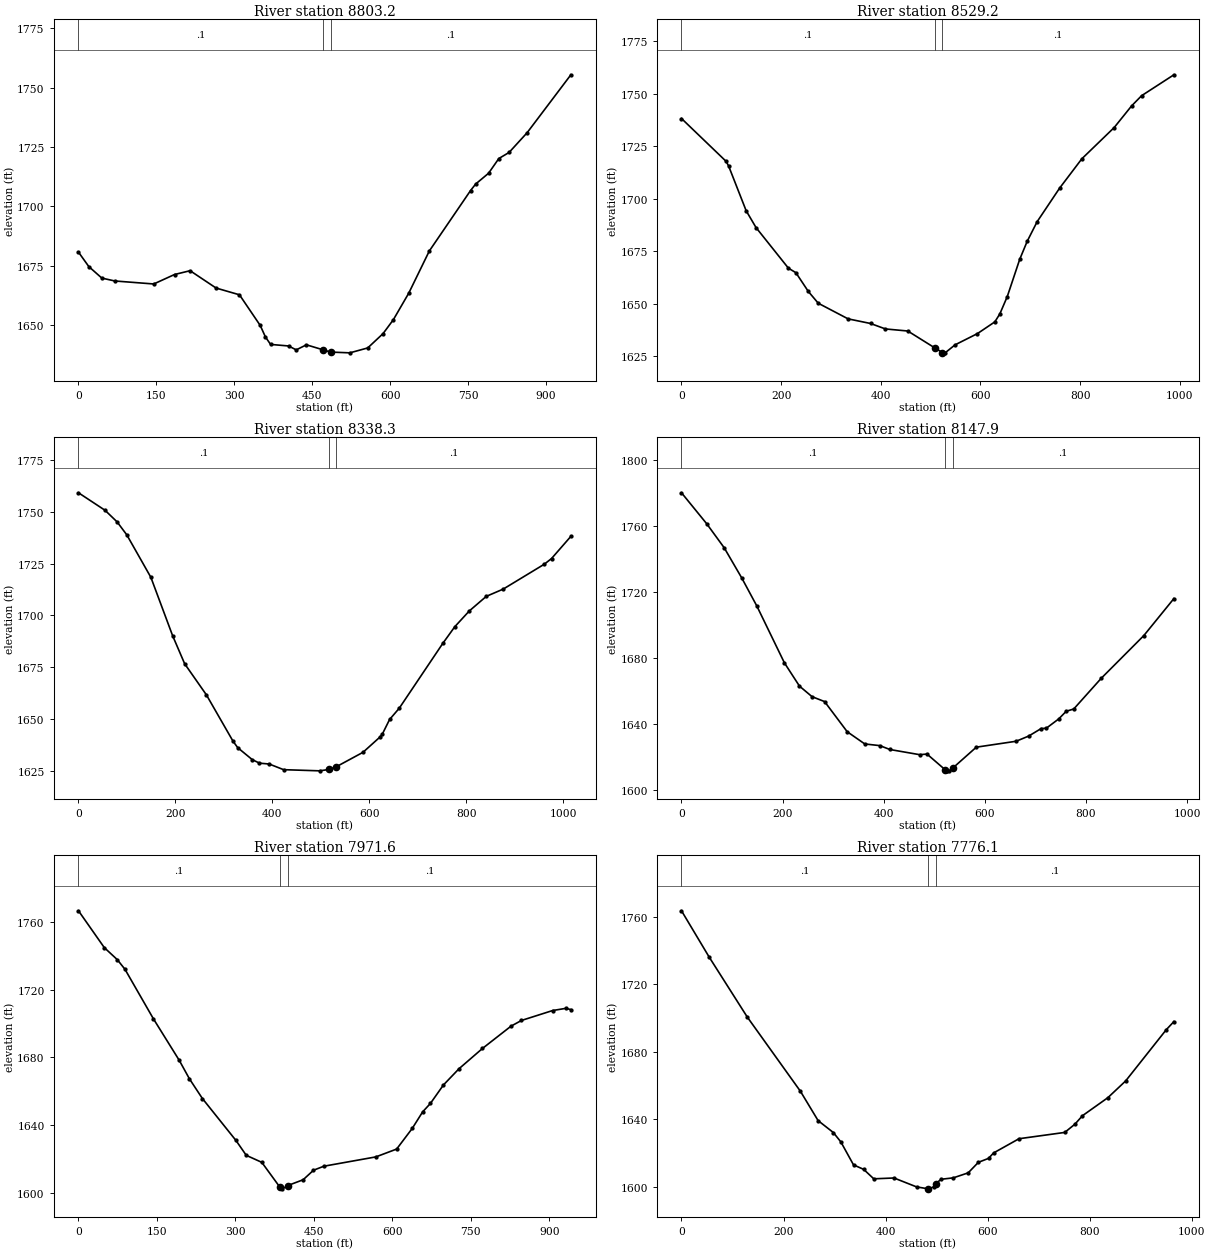
Type RM Length L Ch R = 1 ,8803.2  ,273.5,274,274.5
XS GIS Cut Line= 3
     1800077.119      217053.474     1800048.162      217637.722
     1799816.506      217915.368
#Sta/Elev= 30
       0 1680.79      20 1674.69      45 1669.87      70 1668.66   144.9  1667.4
   184.9 1671.38   214.9 1672.98   264.9 1665.69   309.9 1662.85   349.9 1649.96
   359.8 1645.17   369.8 1641.99   404.4 1641.34   419.2  1639.7   438.8 1641.82
   470.2 1639.77   485.2 1638.77   522.4 1638.45   556.8 1640.51   586.3 1646.53
   606.1 1652.36   635.8 1663.54   675.4 1681.28   754.7 1706.66   764.6 1709.42
   789.4 1713.94   809.2 1720.14     829 1722.71   863.7    1731   947.9 1755.35
#Mann= 3 , 0 , 0
       0      .1       0   470.2    .045       0   485.2      .1       0
Bank Sta=470.2,485.2
XS Rating Curve= 0 ,0
Exp/Cntr=0.3,0.1

Type RM Length L Ch R = 1 ,8529.2  ,215.8,190.9,166
XS GIS Cut Line= 2
     1799922.682      216882.761     1799773.917      217859.807
#Sta/Elev= 30
       0 1738.26    89.8 1717.78    94.8  1715.5   129.8 1694.29   149.7 1686.25
   214.6 1666.93   229.6 1664.78   254.6 1655.82   274.5 1650.22   334.4 1642.77
   379.4 1640.57   409.3 1637.97   454.2 1636.98   508.6 1628.91   523.6 1626.73
   529.1 1626.58   549.1 1630.39     594 1635.75   628.9 1641.34   638.9 1645.11
   653.9 1653.42   678.8 1671.12   693.8 1679.72   713.8 1689.08   758.7 1705.01
   803.6 1719.08   868.5 1733.97   903.4 1744.27   923.4 1749.12   988.3  1759.1
#Mann= 3 , 0 , 0
       0      .1       0   508.6    .045       0   523.6      .1       0
Bank Sta=508.6,523.6
XS Rating Curve= 0 ,0
Exp/Cntr=0.3,0.1

Type RM Length L Ch R = 1 ,8338.3  ,154.9,190.4,225.9
XS GIS Cut Line= 4
      1799573.77      216942.753     1799608.765      217389.398
     1799710.093      217468.871     1799592.507      217891.518
#Sta/Elev= 30
       0 1759.11    54.8 1750.67    79.6  1745.1    99.6 1738.85   149.3 1718.37
   194.1 1690.27     219 1676.71   263.8 1661.74   318.6 1639.45   328.5 1636.26
   358.4 1630.52   373.3 1628.82   393.3 1628.41   423.1 1625.68   497.5 1625.12
   516.9  1625.8   531.9 1627.11   586.8 1634.05   621.7 1641.39   626.6 1642.79
   641.6 1649.86   661.5 1655.28   751.3 1686.52   776.2  1694.6   806.1 1702.19
     841 1709.19   875.9 1712.69   960.6 1724.68   975.6 1727.42  1015.5 1738.11
#Mann= 3 , 0 , 0
       0      .1       0   516.9    .045       0   531.9      .1       0
Bank Sta=516.9,531.9
XS Rating Curve= 0 ,0
Exp/Cntr=0.3,0.1

Type RM Length L Ch R = 1 ,8147.9  ,192.6,176.3,160.1
XS GIS Cut Line= 4
     1799487.178      216960.637     1799560.422      217386.474
     1799456.518      217527.852     1799441.188      217894.072
#Sta/Elev= 30
       0 1779.93    49.7 1761.22    84.4 1746.62   119.2 1728.28     149  1711.3
   203.6 1676.79   233.4 1662.69   258.3 1656.29   283.1 1653.31   327.8 1635.04
   362.6 1627.62   392.4 1626.61   412.2 1624.26   471.1 1621.12   485.7 1621.49
   521.2 1612.08   524.7 1611.32   529.6 1611.36   536.2 1612.87   583.2 1625.67
     662 1629.26   686.8  1632.4   711.6 1636.98   721.5 1637.12   746.2 1642.79
   761.1 1647.44     776 1648.83   830.4 1667.45   914.6 1693.34   974.1 1715.79
#Mann= 3 , 0 , 0
       0      .1       0   521.2    .045       0   536.2      .1       0
Bank Sta=521.2,536.2
XS Rating Curve= 0 ,0
Exp/Cntr=0.3,0.1

Type RM Length L Ch R = 1 ,7971.6  ,193.3,195.4,197.5
XS GIS Cut Line= 4
      1799373.92      216965.469     1799362.401      217286.084
     1799370.348      217439.069     1799292.862      217900.009
#Sta/Elev= 30
       0 1766.75    49.4 1744.95      74 1737.91    88.8 1732.19   143.1 1702.93
   192.5 1678.37   212.2 1667.31   236.9  1655.7   301.1 1630.88   320.8 1622.09
   350.5 1617.94   385.3 1603.16     390 1602.27   400.3 1604.24   429.5 1607.64
   449.3 1613.27   469.1 1615.65   568.5 1621.16   608.3  1625.8   638.1 1638.01
     658  1647.8   672.9 1652.81   697.8 1663.73   727.6 1673.34   772.4 1685.32
     827 1698.51   846.9 1701.87   906.6 1707.75   931.5 1709.02   941.4 1708.32
#Mann= 3 , 0 , 0
       0      .1       0   385.3    .045       0   400.3      .1       0
Bank Sta=385.3,400.3
XS Rating Curve= 0 ,0
Exp/Cntr=0.3,0.1

Type RM Length L Ch R = 1 ,7776.1  ,165.2,167.7,170.3
XS GIS Cut Line= 4
     1799344.441      216962.526     1799197.331      217383.921
     1799192.221      217489.528     1799107.083      217893.769
#Sta/Elev= 30
       0 1763.51    54.6 1735.89   128.9 1700.53   233.1 1656.52   267.8 1639.11
   297.6 1632.06   312.4 1626.48   337.2 1612.87   357.1 1610.21   376.9 1604.61
   416.6  1605.1   460.8 1599.82   483.4 1598.69   484.8 1598.67   494.4 1599.87
   498.4 1601.71   508.8 1604.33   532.8 1605.19     562 1608.15   581.9 1614.39
   601.8 1616.72   611.8 1619.96   661.6 1628.38   751.2 1632.11   771.1 1636.98
     786 1642.03   835.8 1652.72   870.6 1662.63   950.2    1693   965.2 1697.82
#Mann= 3 , 0 , 0
       0      .1       0   483.4    .045       0   498.4      .1       0
Bank Sta=483.4,498.4
XS Rating Curve= 0 ,0
Exp/Cntr=0.3,0.1

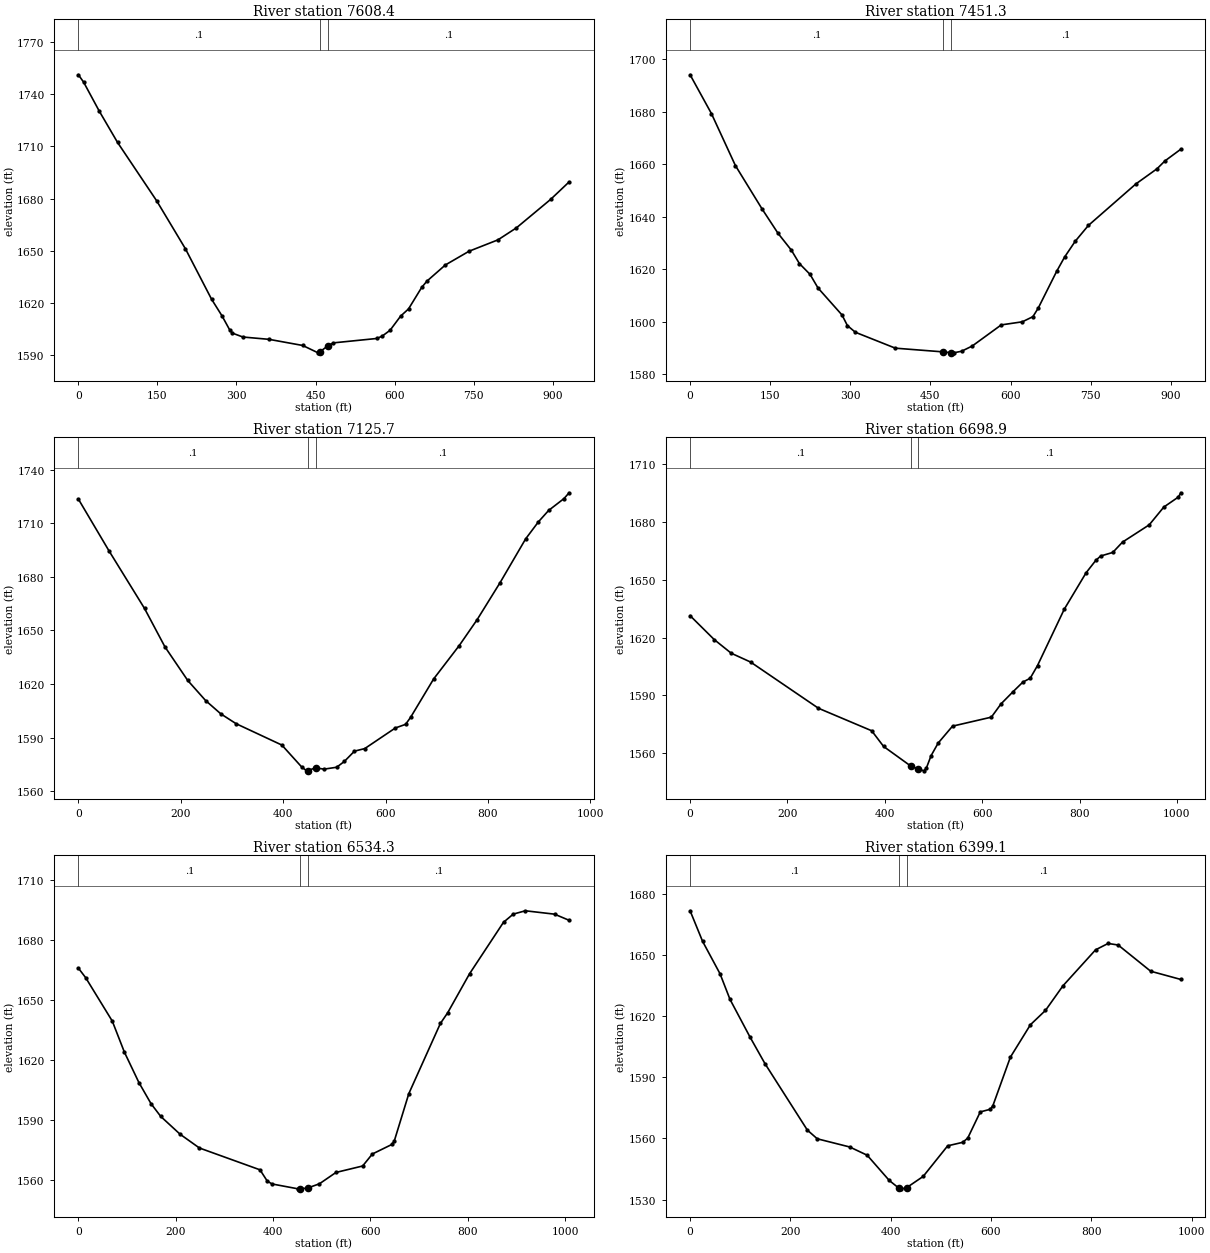
Type RM Length L Ch R = 1 ,7608.4  ,152.7,157.1,161.6
XS GIS Cut Line= 4
     1799179.689      216968.304     1799040.015      217349.853
     1799016.168      217508.265     1799067.268      217869.375
#Sta/Elev= 30
       0 1751.24     9.9 1747.01    39.6 1730.33    74.3 1712.32   148.6 1678.69
   203.2 1651.07   252.7 1622.12   272.5 1612.54   287.4 1604.29   292.4 1602.57
   312.2 1600.34   361.7 1599.01   425.7 1595.48   454.9 1591.24   458.7  1591.9
   473.7 1595.37     484 1596.98   566.5 1599.51   576.5 1600.86   591.5 1604.22
   611.5 1612.37   626.5 1616.51   651.4 1628.84   661.4 1632.49   696.4  1641.8
   741.4 1649.71   796.3 1656.26   831.3 1663.17   896.2 1679.54   931.2 1689.57
#Mann= 3 , 0 , 0
       0      .1       0   458.7    .045       0   473.7      .1       0
Bank Sta=458.7,473.7
XS Rating Curve= 0 ,0
Exp/Cntr=0.3,0.1

Type RM Length L Ch R = 1 ,7451.3  ,333.7,325.6,316.9
XS GIS Cut Line= 4
     1799032.106      216959.787     1798911.168      217314.083
     1798853.254      217472.494     1798826.001      217847.231
#Sta/Elev= 30
       0 1694.16    39.9 1679.39    84.9 1659.53   134.8    1643   164.7 1633.71
   189.7 1627.28   204.6 1622.21   224.6 1618.07   239.6 1612.86   284.5 1602.58
   294.5 1598.56   309.5    1596   384.3 1589.94     474 1588.52     489 1588.19
   493.4 1588.16   508.3 1588.77   528.2 1590.75   582.6 1598.81   622.1 1599.99
   641.9 1601.95   651.8 1605.19   686.4 1619.24   701.2 1624.66     721 1630.66
   745.7 1636.71   834.7 1652.55   874.3 1658.33   889.1 1661.32   918.8 1665.78
#Mann= 3 , 0 , 0
       0      .1       0     474    .045       0     489      .1       0
Bank Sta=474,489
XS Rating Curve= 0 ,0
Exp/Cntr=0.3,0.1

Type RM Length L Ch R = 1 ,7125.7  ,432,426.8,416.1
XS GIS Cut Line= 4
     1798727.207      216888.246     1798594.346      217268.093
     1798590.939      217354.964     1798636.929      217821.681
#Sta/Elev= 30
       0 1723.55    59.6 1694.67   129.2 1662.31   168.9 1640.89   213.6    1622
   248.4 1610.79   278.2  1603.3     308 1597.81   397.4 1585.84   436.2 1573.53
   445.9 1571.41   448.2 1571.59   463.2 1573.09   479.7 1572.36   504.3 1573.41
   519.3 1576.64   539.2 1582.44   559.2 1583.86   619.1 1595.42     639 1597.44
     649 1601.46   693.9 1622.91   743.8 1641.56   778.7 1656.04   823.6 1676.81
   873.5  1701.3   898.5 1710.86   918.4 1717.22   948.4 1723.86   958.3  1727.1
#Mann= 3 , 0 , 0
       0      .1       0   448.2    .045       0   463.2      .1       0
Bank Sta=448.2,463.2
XS Rating Curve= 0 ,0
Exp/Cntr=0.3,0.1

Type RM Length L Ch R = 1 ,6698.9  ,165,164.6,164.3
XS GIS Cut Line= 4
     1798402.034      216858.803     1798228.126      217199.959
      1798242.29      217350.353     1798398.461      217797.834
#Sta/Elev= 30
       0 1631.35    49.7 1618.91    84.5 1611.86   124.3 1607.28   263.6 1583.32
     373 1571.64   397.5 1563.49   453.6 1553.27   468.6 1551.83   480.4 1550.85
   485.3 1552.28     495 1558.72   509.6 1565.28     539 1574.03   618.8  1578.7
   638.8 1585.63   663.7 1591.99   683.6  1596.9   698.6 1598.88   713.6 1605.47
   768.5 1634.67   813.4  1653.6   833.3 1660.02   843.3 1662.29   868.2 1664.15
   888.2 1669.51   943.1 1678.47     973 1687.68    1003  1692.9  1007.9  1695.1
#Mann= 3 , 0 , 0
       0      .1       0   453.6    .045       0   468.6      .1       0
Bank Sta=453.6,468.6
XS Rating Curve= 0 ,0
Exp/Cntr=0.3,0.1

Type RM Length L Ch R = 1 ,6534.3  ,145.5,135.2,124.9
XS GIS Cut Line= 4
     1798243.993      216865.973     1798070.085      217207.129
     1798084.249      217357.523      1798240.42      217805.004
#Sta/Elev= 30
       0 1665.84    14.9  1661.1    69.6 1639.37    94.5 1623.83   124.3 1608.63
   149.2 1598.06   169.1 1591.69   208.9 1582.77   248.6 1575.89     373 1564.97
   387.8  1559.4   397.5 1557.91   451.2 1555.46   455.8 1555.47   470.8 1555.87
     495 1557.97   529.1 1563.66   583.9 1566.89   603.8 1572.88   643.7 1577.64
   648.7 1579.27   678.7 1603.07   743.5 1638.16   758.5 1643.51   803.4 1663.01
   873.2 1688.79   893.2 1692.87   918.1 1694.54     978 1692.85  1007.9 1689.78
#Mann= 3 , 0 , 0
       0      .1       0   455.8    .045       0   470.8      .1       0
Bank Sta=455.8,470.8
XS Rating Curve= 0 ,0
Exp/Cntr=0.3,0.1

Type RM Length L Ch R = 1 ,6399.1  ,485.4,469.6,453.8
XS GIS Cut Line= 4
     1797791.719       216952.34      1797930.04      217298.753
      1797991.36      217402.657     1798129.989      217867.162
#Sta/Elev= 30
       0 1671.86    24.9 1656.85    59.7 1640.91    79.6 1628.32   119.4 1609.86
   149.2 1596.81   233.8 1564.12   253.6 1559.85   318.3 1555.83   353.1 1551.78
   397.1 1539.39   417.1 1535.45   421.3 1535.27   432.1  1535.9   464.7 1541.36
   513.6  1556.4   543.6 1558.12   553.6  1560.2   578.6 1573.06   598.6 1574.36
   603.6 1576.02   638.6 1599.94   678.6 1615.88   708.6 1622.92   743.5 1635.02
   808.5 1652.68   833.5 1655.81   853.5 1655.04   918.4 1642.16   978.4 1638.13
#Mann= 3 , 0 , 0
       0      .1       0   417.1    .045       0   432.1      .1       0
Bank Sta=417.1,432.1
XS Rating Curve= 0 ,0
Exp/Cntr=0.3,0.1

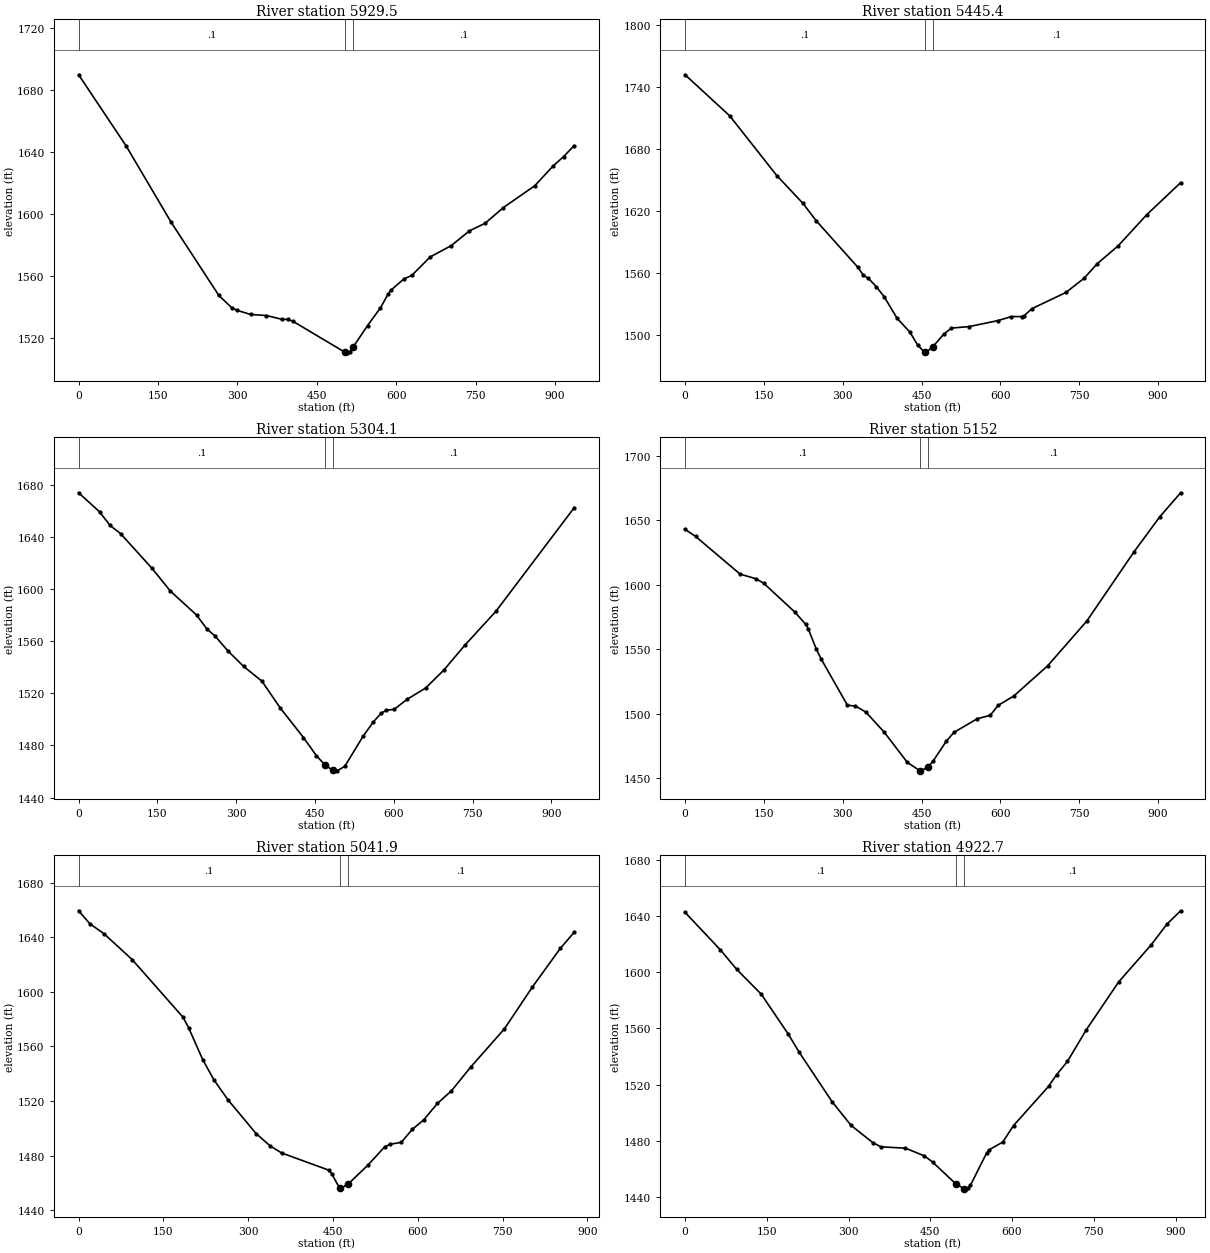
Type RM Length L Ch R = 1 ,5929.5  ,481.3,484,486.8
XS GIS Cut Line= 4
      1797314.58      217421.328     1797643.878      217664.973
     1797803.992      217722.887     1798115.717      217895.289
#Sta/Elev= 30
       0 1689.66    89.9 1643.63   174.8  1594.4   264.8 1547.21   289.7 1539.09
   299.7 1537.54   324.7 1534.91   354.7 1534.21   384.7 1531.72   394.6 1531.71
   404.6 1530.54     503 1510.52   506.9 1510.12   511.8 1510.77     518 1513.61
   545.8 1527.72   570.2 1539.21   584.8 1548.16   589.8 1550.54   614.5 1557.85
   629.4 1560.13     664 1572.01   703.6 1579.29   738.2 1588.86   767.9 1593.78
   802.5 1603.94   861.9 1618.08   896.5 1630.85   916.3 1636.88   936.1 1643.93
#Mann= 3 , 0 , 0
       0      .1       0     503    .045       0     518      .1       0
Bank Sta=503,518
XS Rating Curve= 0 ,0
Exp/Cntr=0.3,0.1

Type RM Length L Ch R = 1 ,5445.4  ,141.4,141.4,141.5
XS GIS Cut Line= 4
     1797028.952      217719.819     1797310.021      217966.465
     1797446.289      218034.599     1797786.696      218275.235
#Sta/Elev= 30
       0 1751.94    84.8 1712.23   174.5 1654.34   224.4 1627.37   249.3  1610.7
   329.1 1565.37     339 1557.98     349 1554.72     364 1546.68   378.9 1536.98
   403.4 1516.16     428 1502.63   442.8 1490.06   456.2 1483.06   457.5 1482.64
   471.2 1488.38   491.9 1500.49   506.6 1506.56   541.2 1508.14   595.8 1513.89
   620.6 1517.73   640.4 1517.78   645.4  1518.7   660.3 1525.46   724.8 1541.08
   759.6 1554.94   784.4 1568.96   824.1 1586.18   878.6 1616.39   943.2 1647.47
#Mann= 3 , 0 , 0
       0      .1       0   456.2    .045       0   471.2      .1       0
Bank Sta=456.2,471.2
XS Rating Curve= 0 ,0
Exp/Cntr=0.3,0.1

Type RM Length L Ch R = 1 ,5304.1  ,152,152.1,152.1
XS GIS Cut Line= 4
      1796994.73      217852.771     1797275.799      218099.418
     1797412.067      218167.552     1797752.474      218408.187
#Sta/Elev= 30
       0 1673.95    39.9 1659.29    59.8  1648.9    79.8  1642.6   139.6    1616
   174.5 1598.56   224.4 1580.15   244.3 1569.34   259.3 1564.16   284.2 1552.58
   314.1 1540.67     349 1529.31   383.8 1508.76     428 1486.08   452.6 1472.18
   468.8  1465.1   483.8 1460.98   491.9 1460.54   506.6 1464.01   541.2 1486.95
     561 1498.09   575.9  1504.8   585.8 1507.01   600.7 1507.78   625.6 1515.54
   660.3 1524.04     695  1537.8   734.7 1556.77   794.3 1583.02   943.2 1662.47
#Mann= 3 , 0 , 0
       0      .1       0   468.8    .045       0   483.8      .1       0
Bank Sta=468.8,483.8
XS Rating Curve= 0 ,0
Exp/Cntr=0.3,0.1

Type RM Length L Ch R = 1 ,5152    ,109.5,110.1,110.8
XS GIS Cut Line= 4
     1796941.086      217989.861     1797222.156      218236.508
     1797358.423      218304.642      1797698.83      218545.277
#Sta/Elev= 30
       0  1642.9    19.9 1637.44   104.7  1608.2   134.6 1604.64   149.6 1601.15
   209.4 1578.51   229.4 1569.35   234.3 1565.84   249.3 1550.45   259.3 1542.12
   309.1  1506.4   324.1 1505.92     344 1501.21   378.9 1485.65   423.1 1462.12
   446.6 1455.79   447.7 1455.61   461.6 1458.23   472.2 1463.24   496.8 1478.42
   511.6  1485.4   556.1 1496.02   580.9 1498.71   595.8 1506.38   625.6 1513.63
   690.1 1537.09   764.5 1571.74   853.8  1625.1   903.5 1652.66   943.2 1671.28
#Mann= 3 , 0 , 0
       0      .1       0   446.6    .045       0   461.6      .1       0
Bank Sta=446.6,461.6
XS Rating Curve= 0 ,0
Exp/Cntr=0.3,0.1

Type RM Length L Ch R = 1 ,5041.9  ,114.1,119.1,124.2
XS GIS Cut Line= 4
     1796888.586      218084.313     1797169.655       218330.96
     1797305.923      218399.094     1797591.986      218601.313
#Sta/Elev= 30
       0 1659.43    19.9  1649.9    44.9 1642.61    94.7 1623.66   184.5 1581.51
   194.4 1573.88   219.4 1550.44   239.3 1535.52   264.2 1520.89   314.1 1496.08
     339 1487.08     359 1481.97   442.8 1469.31   447.7 1466.71   461.8 1456.02
   462.4 1455.66   476.8 1459.17   511.6 1472.97   541.1 1486.32     551 1488.33
   570.7 1489.74   590.4 1499.34   610.2 1506.07   634.8 1518.31   659.5 1527.48
   694.1 1545.16   753.3 1572.96   802.6 1603.53     852 1631.81   876.6  1643.7
#Mann= 3 , 0 , 0
       0      .1       0   461.8    .045       0   476.8      .1       0
Bank Sta=461.8,476.8
XS Rating Curve= 0 ,0
Exp/Cntr=0.3,0.1

Type RM Length L Ch R = 1 ,4922.7  ,476,487.2,498.5
XS GIS Cut Line= 4
     1796846.711      218135.097     1797153.313      218421.259
     1797304.911       218549.01     1797591.986      218601.313
#Sta/Elev= 30
       0 1642.54    64.9 1615.82    94.9  1601.9   139.8 1584.29   189.7 1555.68
   209.7  1542.8   269.6 1507.83   304.6 1490.89   344.5 1478.61   359.5 1475.64
   404.4 1474.67   439.2 1469.18   454.1 1464.81   497.5 1448.99   512.5 1445.82
   513.6 1445.72   518.5 1446.12   523.5 1448.15   553.2 1471.12   558.2 1473.56
     583 1479.02   602.8 1490.81   667.1 1518.71   681.9 1527.06   701.7 1536.49
   736.3 1558.99   795.7 1593.06     855 1619.29   884.7  1634.4   909.4  1643.7
#Mann= 3 , 0 , 0
       0      .1       0   497.5    .045       0   512.5      .1       0
Bank Sta=497.5,512.5
XS Rating Curve= 0 ,0
Exp/Cntr=0.3,0.1