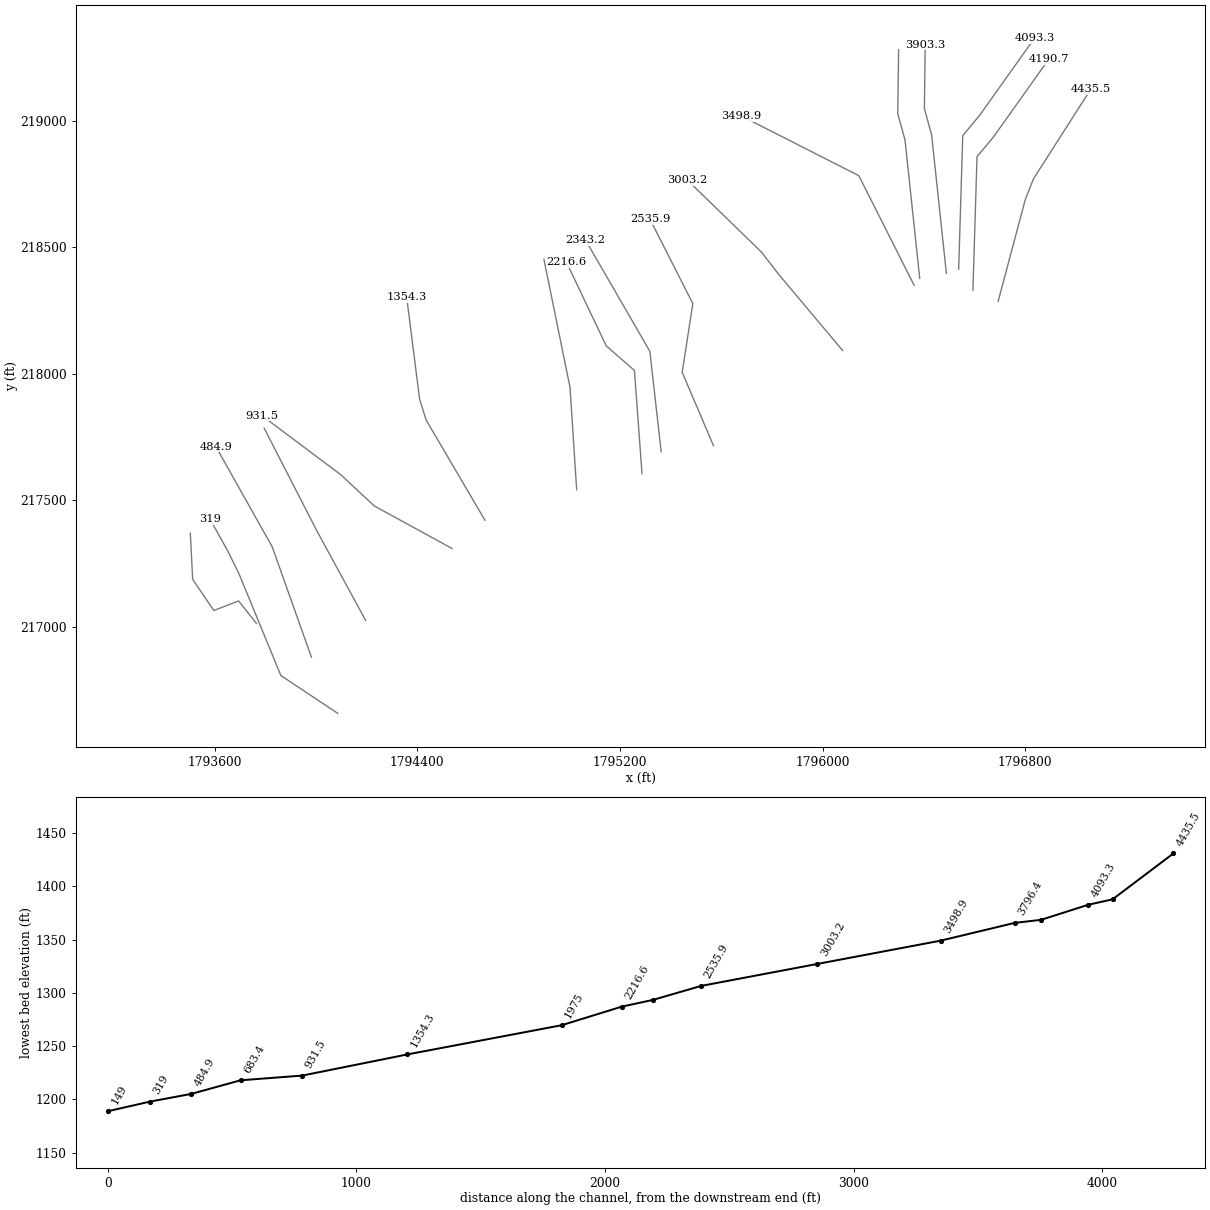
HEC-RAS study SkinFk.prj: SkinFk

--- SkinFk.g01 (geometry) --- (continued)

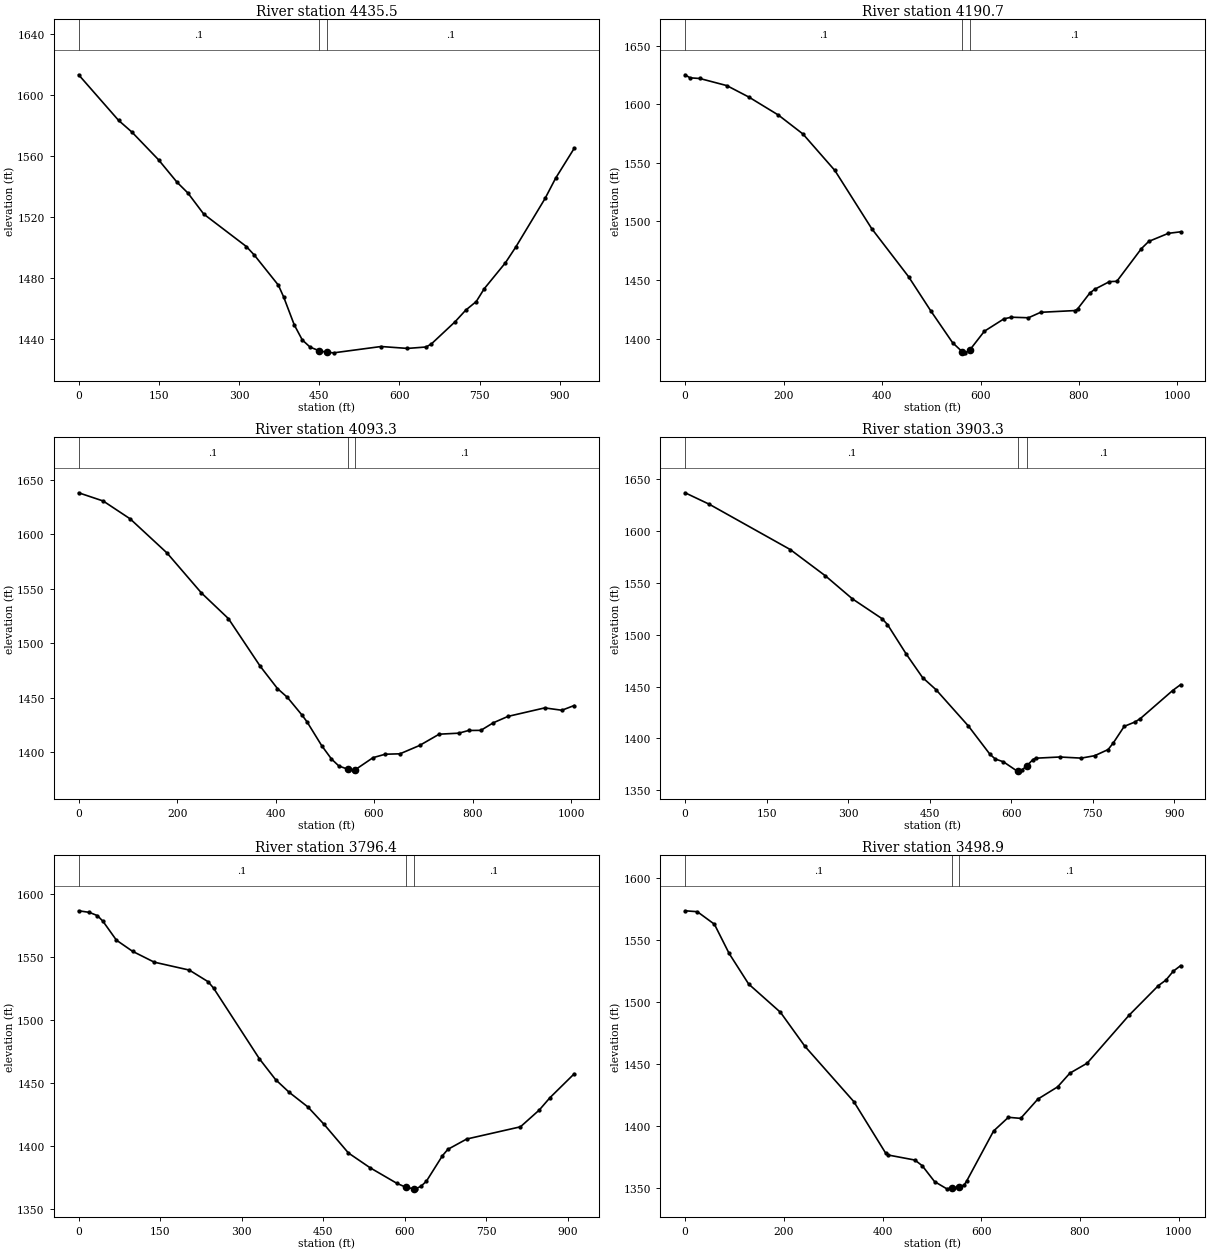
Type RM Length L Ch R = 1 ,4435.5  ,251.9,244.8,237.6
XS GIS Cut Line= 4
     1796693.228      218286.153      1796800.72      218690.388
     1796833.084      218772.149     1797059.491      219126.443
#Sta/Elev= 30
       0 1613.38    74.7 1583.48    99.6 1575.82   149.4 1557.65   184.2 1542.84
   204.2  1535.9     234 1522.02   313.7 1500.74   328.6 1495.13   373.5 1475.42
   383.4 1467.68   403.3 1449.32   418.3 1439.47   432.9 1434.77   449.9 1432.39
   464.9 1431.34   476.9 1431.03   565.6 1435.18     615 1433.93   649.7 1434.86
   659.6 1436.85   704.1 1451.45   723.9 1459.03   743.6 1464.67   758.5 1473.07
   798.1 1490.07   817.8 1500.58   872.3 1532.28     892 1545.55   926.7 1565.11
#Mann= 3 , 0 , 0
       0      .1       0   449.9    .045       0   464.9      .1       0
Bank Sta=449.9,464.9
XS Rating Curve= 0 ,0
Exp/Cntr=0.3,0.1

Type RM Length L Ch R = 1 ,4190.7  ,97.3,97.4,97.4
XS GIS Cut Line= 4
      1796593.82      218330.685     1796609.945       218859.02
     1796676.376      218939.077     1796892.701      219243.976
#Sta/Elev= 30
       0 1625.06      10 1622.46    29.9 1621.89    84.8 1615.82   129.6 1606.04
   189.5  1590.7   239.4 1574.54   304.2 1543.44     379 1493.86   453.8  1452.9
   498.7  1423.9   543.4 1396.51   562.7 1388.92   568.2  1387.9   577.7 1390.02
   607.8 1406.31   647.6 1416.89   662.5 1418.28   697.4 1417.82   722.3 1422.48
   792.1 1423.96   797.1  1425.3     822 1438.87     832 1442.12   861.9 1448.64
   876.9 1448.91   926.7 1476.74   941.7 1482.93   981.5 1489.82  1006.5 1491.13
#Mann= 3 , 0 , 0
       0      .1       0   562.7    .045       0   577.7      .1       0
Bank Sta=562.7,577.7
XS Rating Curve= 0 ,0
Exp/Cntr=0.3,0.1

Type RM Length L Ch R = 1 ,4093.3  ,166.9,190,213
XS GIS Cut Line= 4
     1796537.535      218414.012     1796553.661      218942.347
     1796620.091      219022.405     1796836.416      219327.304
#Sta/Elev= 30
       0 1638.14    49.9 1630.58   104.7 1614.18   179.5 1582.87   249.3 1546.21
   304.2 1522.62     369 1478.75   403.9 1458.36   423.9 1450.35   453.8 1433.98
   463.8 1427.89   493.7 1405.96   513.6 1393.68   528.6 1387.27   546.9 1384.29
   558.3 1382.83   561.9 1383.87   597.9 1394.92   622.7 1398.09   652.6 1398.46
   692.4  1406.1   732.3 1416.48   772.2 1417.42   792.1 1419.89     817    1420
     842  1426.9   871.9  1432.8   946.6 1440.62   981.5 1438.47  1006.5  1442.8
#Mann= 3 , 0 , 0
       0      .1       0   546.9    .045       0   561.9      .1       0
Bank Sta=546.9,561.9
XS Rating Curve= 0 ,0
Exp/Cntr=0.3,0.1

Type RM Length L Ch R = 1 ,3903.3  ,106.9,106.9,106.9
XS GIS Cut Line= 4
     1796489.048      218397.412     1796430.775      218945.162
     1796402.177      219049.795     1796405.584       219301.89
#Sta/Elev= 30
       0 1636.87    44.7 1625.75   193.5 1582.08     258 1556.77   307.7 1534.56
   362.3 1515.41   372.2 1509.81   406.9 1481.17   436.7 1458.68   461.5 1446.92
   521.1 1411.87   560.7 1384.62   570.6 1380.03   585.4 1377.39     610 1368.66
     613 1368.67   619.9 1369.74     628 1373.21   639.6 1379.47   644.5 1380.84
     689 1382.01   728.5 1380.93   753.2 1383.24     778 1389.18   787.8 1395.78
   807.6 1411.54   827.4 1415.79   837.3 1419.06   896.6  1446.1   911.4 1451.83
#Mann= 3 , 0 , 0
       0      .1       0     613    .045       0     628      .1       0
Bank Sta=613,628
XS Rating Curve= 0 ,0
Exp/Cntr=0.3,0.1

Type RM Length L Ch R = 1 ,3796.4  ,278.6,297.5,316.3
XS GIS Cut Line= 4
     1796383.895      218377.598     1796325.623      218925.348
     1796297.025       219029.98     1796300.432      219282.076
#Sta/Elev= 30
       0 1586.71    19.8 1585.44    34.7 1582.82    44.7 1578.39    69.5 1563.35
    99.2  1554.5     139 1545.88   203.5 1539.59   238.2 1530.32   248.1  1525.3
   332.5 1469.07   362.3  1452.5   387.1 1442.51   421.8 1430.76   451.6  1416.9
   496.2 1394.23     536 1382.51   585.4  1370.1   601.2 1367.12   616.2 1365.77
   619.9 1365.74   629.7 1367.81   639.6 1371.78   669.2 1392.11   679.1 1397.13
   713.7 1405.32   812.6 1415.04   847.2 1428.37   866.9  1438.2   911.4 1457.12
#Mann= 3 , 0 , 0
       0      .1       0   601.2    .045       0   616.2      .1       0
Bank Sta=601.2,616.2
XS Rating Curve= 0 ,0
Exp/Cntr=0.3,0.1

Type RM Length L Ch R = 1 ,3498.9  ,505.8,495.7,485.6
XS GIS Cut Line= 3
     1796361.597      218350.526     1796143.228      218784.072
     1795681.131      219019.374
#Sta/Elev= 30
       0 1573.28    24.8 1572.53    59.4 1562.43    89.2 1538.87   128.8 1514.19
   193.2 1491.42   242.7 1464.04   341.8 1419.43   406.2 1377.98   411.1 1376.38
   465.6 1372.29   480.5  1367.7   505.4 1354.93   530.3 1349.08   540.2 1349.86
   555.2 1350.46   565.2 1352.08   570.2 1355.15     625  1395.7     655 1406.75
   679.9  1405.9   714.8 1421.47   754.7 1431.28   779.6 1442.35   814.5 1450.36
   899.3 1488.96   959.1 1513.01   974.1 1517.35     989 1524.52    1004 1529.06
#Mann= 3 , 0 , 0
       0      .1       0   540.2    .045       0   555.2      .1       0
Bank Sta=540.2,555.2
XS Rating Curve= 0 ,0
Exp/Cntr=0.3,0.1

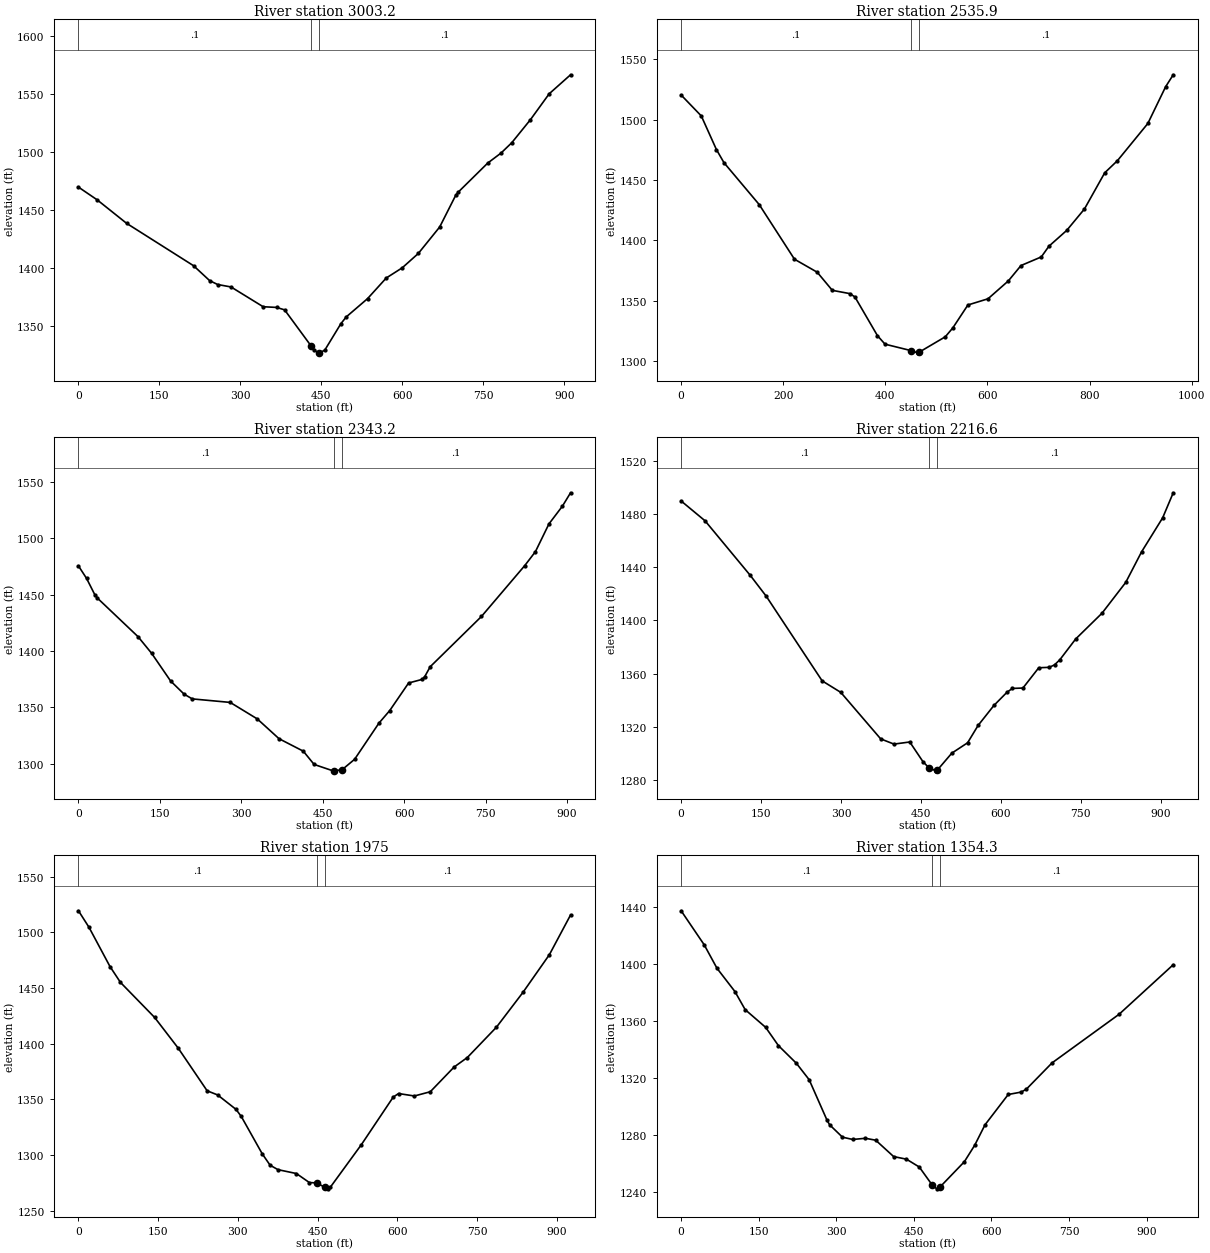
Type RM Length L Ch R = 1 ,3003.2  ,486.1,467.3,448.5
XS GIS Cut Line= 4
     1796079.705      218092.096     1795828.109      218392.302
     1795758.271       218482.58     1795467.582      218765.491
#Sta/Elev= 30
       0  1469.8    34.7 1458.84    89.2 1438.64   213.2 1402.17     243 1389.35
   257.8 1386.01   282.6  1383.9   342.1 1366.89   366.9  1366.3   381.8 1364.21
   430.5  1333.4   436.4 1329.27   445.5 1327.28   446.3 1327.22   456.2 1329.49
     486 1352.23   495.9 1358.09   535.5 1373.86   570.1  1391.6   599.8  1400.4
   629.5 1412.72   669.1  1435.5   698.8 1462.77   703.7 1465.61   758.1  1490.5
   782.8 1499.14   802.6 1507.99   837.3 1527.89   871.9 1550.09   911.5 1566.46
#Mann= 3 , 0 , 0
       0      .1       0   430.5    .045       0   445.5      .1       0
Bank Sta=430.5,445.5
XS Rating Curve= 0 ,0
Exp/Cntr=0.3,0.1

Type RM Length L Ch R = 1 ,2535.9  ,177.2,192.8,208.3
XS GIS Cut Line= 4
     1795569.815      217715.435     1795446.144      218006.014
     1795488.017      218278.187     1795319.482      218610.639
#Sta/Elev= 30
       0 1520.48    39.5 1503.12    69.1 1475.26    83.9 1464.34     153 1429.55
     222 1384.26   266.5 1373.48   296.1 1358.44   330.6 1355.71   340.4 1352.95
   384.6  1320.8   399.4 1313.77   450.3 1308.44   463.3 1306.59   465.3  1306.9
   517.4  1319.9   532.2 1327.29   561.7 1346.29   601.1 1351.43   640.9 1366.25
   665.7 1379.01   705.5 1386.17   720.4 1395.04   755.2 1408.13     790 1425.93
   829.7 1455.94   854.6 1466.01   914.2 1496.89     949 1527.34   963.9 1537.27
#Mann= 3 , 0 , 0
       0      .1       0   450.3    .045       0   465.3      .1       0
Bank Sta=450.3,465.3
XS Rating Curve= 0 ,0
Exp/Cntr=0.3,0.1

Type RM Length L Ch R = 1 ,2343.2  ,119.1,126.5,134
XS GIS Cut Line= 3
     1795363.095      217692.226     1795318.436      218089.146
     1795065.009       218528.57
#Sta/Elev= 30
       0  1475.5      15 1464.36      30 1450.03      35 1446.87   109.8 1412.65
   134.8 1397.89   169.8  1373.3   194.7  1361.6   209.7 1357.41   279.6 1354.28
   329.5 1339.62   369.5 1322.08   414.3 1310.97   434.2  1299.2     469 1293.52
   470.6 1293.53   485.6 1294.46   508.8 1303.76   553.6 1335.86   573.5 1347.02
   608.3 1371.52   633.2 1374.72   638.1 1377.26   648.1 1385.96   742.6 1430.64
   822.2 1475.71     842 1488.18   866.9  1512.8   891.8 1528.63   906.7 1540.44
#Mann= 3 , 0 , 0
       0      .1       0   470.6    .045       0   485.6      .1       0
Bank Sta=470.6,485.6
XS Rating Curve= 0 ,0
Exp/Cntr=0.3,0.1

Type RM Length L Ch R = 1 ,2216.6  ,262.1,241.7,221.3
XS GIS Cut Line= 4
     1795287.482      217605.019     1795257.648      218013.257
     1795146.386      218110.611     1794989.396      218441.363
#Sta/Elev= 30
       0 1489.64    44.9 1474.75   129.8 1433.76   159.7 1418.14   264.6 1354.64
   299.5 1346.02   374.4 1311.11   399.3 1307.19     429 1308.77   453.7 1294.02
   465.4  1289.2   478.3 1287.12   480.4 1287.54   507.9  1300.4   537.5 1308.18
   557.2  1321.2   586.8 1336.16   611.6 1346.18   621.5 1348.97   641.3 1349.26
     671 1364.48   690.8  1364.8   700.6 1366.67   710.5 1370.45   740.2 1386.04
   789.7 1405.43   834.2 1428.54   863.9 1451.45   903.5 1477.02   923.3 1495.79
#Mann= 3 , 0 , 0
       0      .1       0   465.4    .045       0   480.4      .1       0
Bank Sta=465.4,480.4
XS Rating Curve= 0 ,0
Exp/Cntr=0.3,0.1

Type RM Length L Ch R = 1 ,1975    ,614.2,620.7,627.1
XS GIS Cut Line= 3
     1795029.537      217541.776     1795003.353      217946.025
     1794900.169       218453.49
#Sta/Elev= 30
       0 1519.24    19.8 1504.44    59.3 1469.21      79 1454.96   143.3  1423.5
   187.7 1395.93   242.1 1357.66   261.8 1353.96   296.4    1341   306.3 1334.65
   345.8 1301.06   360.6 1290.84   375.4 1286.88     410 1283.41   434.4 1275.32
   448.7 1274.99   463.7  1270.9   468.6 1269.67   473.5 1270.88   532.4 1309.43
   592.2 1352.04   602.2  1355.2     632 1353.01   661.9 1356.81   706.7 1378.99
   731.6 1387.53   786.4 1414.77   836.2 1445.96     886 1479.85   925.8 1515.46
#Mann= 3 , 0 , 0
       0      .1       0   448.7    .045       0   463.7      .1       0
Bank Sta=448.7,463.7
XS Rating Curve= 0 ,0
Exp/Cntr=0.3,0.1

Type RM Length L Ch R = 1 ,1354.3  ,410.9,422.8,434.7
XS GIS Cut Line= 4
     1794667.402      217421.009      1794434.77      217818.274
      1794409.22      217901.738     1794358.613      218302.331
#Sta/Elev= 30
       0 1437.29    44.6 1413.42    69.3 1396.97     104 1380.64   123.8 1367.94
   163.4 1355.52   188.1 1342.71   222.8 1330.32   247.5 1318.81   282.2 1290.28
   287.1 1287.17   311.9 1278.48   331.7 1276.88   356.4  1277.7   376.2 1276.35
   410.9 1264.86   435.6 1263.05   460.4 1257.55   485.6 1244.83   494.3 1242.24
   500.6 1243.56   547.6 1261.27   567.6 1272.83   587.5 1287.15   632.4 1308.42
   657.3  1310.1   667.3  1312.1   717.1 1330.58   846.8 1364.71   951.4 1399.45
#Mann= 3 , 0 , 0
       0      .1       0   485.6    .045       0   500.6      .1       0
Bank Sta=485.6,500.6
XS Rating Curve= 0 ,0
Exp/Cntr=0.3,0.1

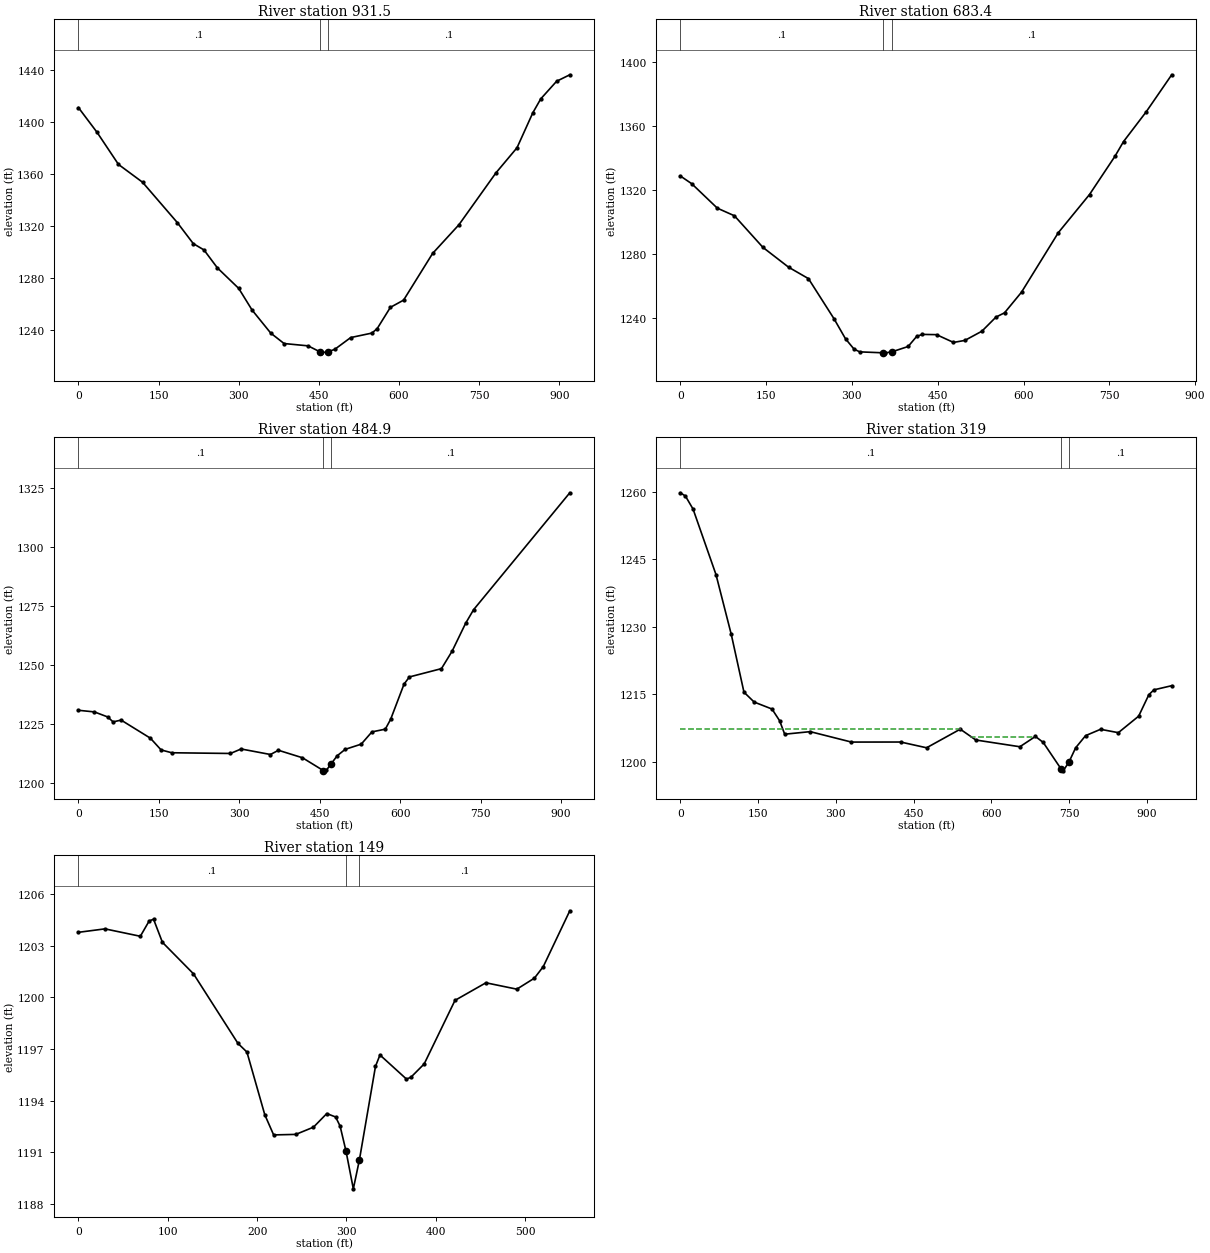
Type RM Length L Ch R = 1 ,931.5   ,255.4,248.1,240.7
XS GIS Cut Line= 4
     1794537.211      217309.295     1794230.369      217477.605
     1794099.211      217600.246     1793787.281      217834.543
#Sta/Elev= 30
       0 1411.38      35 1392.24      75 1367.56     120 1353.86     185  1322.8
     215 1306.53     235 1301.68     260 1287.89     300 1272.04     325 1255.37
     360 1237.56   384.9 1229.54   429.8 1227.76   452.1 1223.14   454.7 1222.37
   467.1 1223.26   479.7 1225.05   509.6 1234.14   549.3  1237.6   559.2 1241.05
   583.9 1257.43   608.6    1263   662.9 1298.97   712.2  1321.1   781.4 1361.05
   820.9 1380.44   850.5  1407.4   865.3  1418.1     895 1431.68   919.7 1436.67
#Mann= 3 , 0 , 0
       0      .1       0   452.1    .045       0   467.1      .1       0
Bank Sta=452.1,467.1
XS Rating Curve= 0 ,0
Exp/Cntr=0.3,0.1

Type RM Length L Ch R = 1 ,683.4   ,202,198.5,198.9
XS GIS Cut Line= 3
     1794196.411      217024.685     1794001.548       217383.44
     1793796.133      217784.761
#Sta/Elev= 30
       0 1328.65    19.9 1323.81    64.7  1308.5    94.6 1303.73   144.4 1283.96
   189.2 1271.57     224  1264.4   268.8 1239.23   288.8 1226.74   303.7 1220.28
   313.7 1218.56   354.9 1217.96   358.5 1217.95   369.9 1218.58   398.3 1221.92
   413.2 1228.23   423.1 1229.49   447.9 1229.33   477.6 1224.47   497.4 1225.72
   527.2 1231.48   551.9 1240.34   566.8 1242.99   596.5 1255.91   660.9 1293.18
   715.4 1317.04     760 1341.04   774.9 1350.19   814.5  1368.8   859.1 1391.98
#Mann= 3 , 0 , 0
       0      .1       0   354.9    .045       0   369.9      .1       0
Bank Sta=354.9,369.9
XS Rating Curve= 0 ,0
Exp/Cntr=0.3,0.1

Type RM Length L Ch R = 1 ,484.9   ,163.5,165.9,164.5
XS GIS Cut Line= 3
     1793982.253       216879.41      1793827.93      217315.331
     1793605.911      217710.984
#Sta/Elev= 30
       0 1230.78    29.8 1230.09    54.7 1227.95    64.6 1225.87    79.6 1226.63
   134.2 1218.97   154.1 1214.01     174 1212.81   283.4 1212.51   303.3 1214.41
     358 1212.07   372.9 1213.86   417.7 1210.69   456.6 1205.27   457.5 1205.16
   462.4 1205.47   471.6 1208.25   482.4 1211.54   497.3 1214.25   527.2 1216.45
   547.2 1221.64   572.1 1222.79   582.1 1226.97     607 1241.82     617 1244.88
   676.8  1248.4   696.8 1255.84   721.7 1267.51   736.6  1273.3   916.1  1322.8
#Mann= 3 , 0 , 0
       0      .1       0   456.6    .045       0   471.6      .1       0
Bank Sta=456.6,471.6
XS Rating Curve= 0 ,0
Exp/Cntr=0.3,0.1

Type RM Length L Ch R = 1 ,319     ,166.9,169.9,173
XS GIS Cut Line= 5
     1794086.495       216656.82     1793861.653      216806.714
     1793696.537      217209.125     1793651.977      217299.517
     1793583.012      217423.913
#Sta/Elev= 30
       0 1259.79     9.8 1259.07    24.6 1256.16    68.8  1241.6    98.3 1228.29
   122.8 1215.43   142.5 1213.23   176.9 1211.68   191.6 1209.08   201.4 1206.08
   250.6 1206.65   330.2 1204.33   425.2 1204.34   475.2 1203.06   540.2  1207.2
   570.2 1204.79   655.2 1203.29   685.2 1205.58   700.2 1204.26   734.9 1198.32
   738.8 1197.93   749.9 1199.88   762.8 1203.05     782 1205.76   810.9 1207.17
   845.2 1206.42   884.4 1210.09   904.1 1214.87   913.9 1215.95   948.2 1216.87
#Mann= 3 , 0 , 0
       0      .1       0   734.9    .045       0   749.9      .1       0
#XS Ineff= 2 ,-1
       0  541.19 1207.18  559.79  684.681205.561
Permanent Ineff=
       F       F
Bank Sta=734.9,749.9
XS Rating Curve= 0 ,0
Exp/Cntr=0.3,0.1

Type RM Length L Ch R = 1 ,149     ,146.8,149,151.3
XS GIS Cut Line= 5
     1793765.469      217012.328     1793694.866      217101.582
     1793597.194      217063.813     1793513.695      217186.838
      1793504.37      217369.341
#Sta/Elev= 30
       0 1203.77    29.7 1203.97    69.3 1203.54    79.2 1204.43    84.1 1204.53
      94 1203.19   128.8 1201.36   178.6 1197.32   188.6 1196.82   208.6 1193.18
   218.5 1192.01   243.3 1192.04   263.1 1192.46     278 1193.25   287.9 1193.05
   292.9 1192.52   299.5 1191.07   307.7 1188.88   314.5 1190.56   332.5 1195.99
   337.5 1196.65   367.2 1195.25   372.2 1195.36     387 1196.13   421.5 1199.82
   456.1 1200.84   490.7 1200.47   510.4 1201.11   520.3 1201.78     550 1205.02
#Mann= 3 , 0 , 0
       0      .1       0   299.5    .045       0   314.5      .1       0
Bank Sta=299.5,314.5
XS Rating Curve= 0 ,0
Exp/Cntr=0.3,0.1

Chan Stop Cuts=-1
Use User Specified Reach Order=0